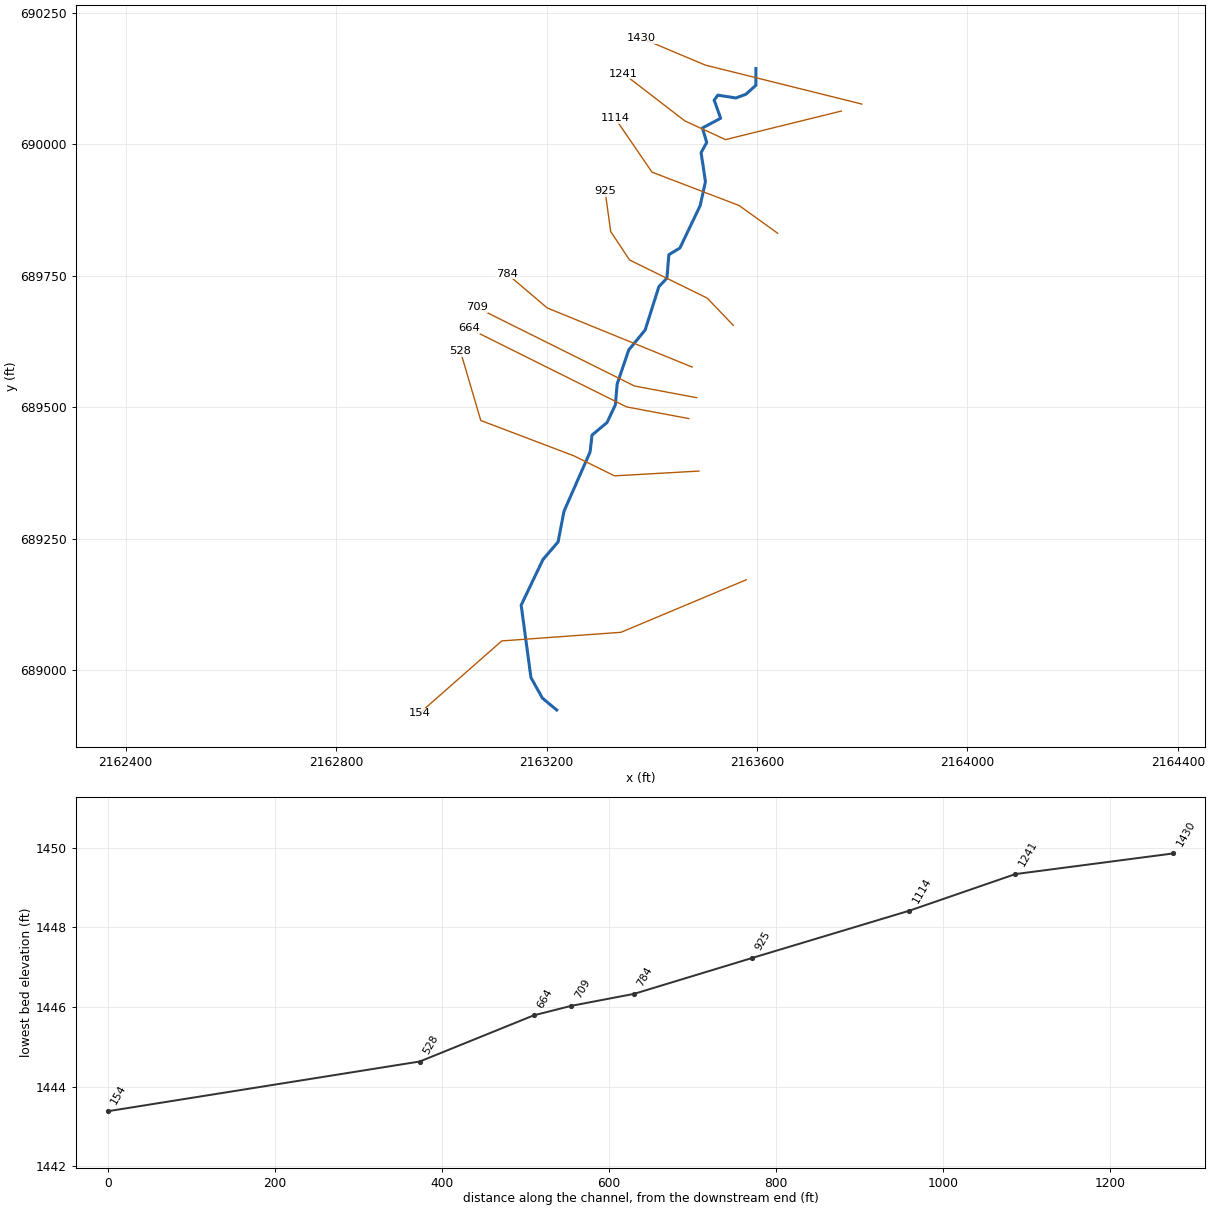
--- SLABCPFKT1.prj (project) ---

Proj Title=SLABCPFKT1
Current Plan=p01
Default Exp/Contr=0,0
English Units
Geom File=g01
Flow File=f01
Plan File=p01
BEGIN DESCRIPTION:
---------- MODELED AS PART OF WVEMD CTP PROGRAM, 2023----------
Stream Name: Slab Camp Fork Tributary 1
Flood Zone:  AFH
Upshur County, WV
HEC-RAS Version: RAS 6.3
Vertical Datum: NAVD88
Projection: NAD 1983 StatePlane West Virginia S FIPS 4702 (US Feet)
Terrain: 1-meter LIDAR (FEMA Region III 3DEP collected 2016-2018)
Land Use: 2019 NLCD
Hydrologic Method:
WV SIR2010-5033 regression equations
Additional Model Notes:
Main stem is SLABCMPFK
END DESCRIPTION:
DSS Export Rating Curves= 0
DSS Export Rating Curve Sorted= 0
DSS Export Volume Flow Curves= 0
DXF OffsetX= 0
DXF OffsetY= 0
DXF ScaleX= 0
DXF ScaleY= 0

--- SLABCPFKT1.p01 (plan) ---

Plan Title=Floodplain
Program Version=6.31
Short Identifier=Floodplain
Geom File=g01
Flow File=f01
Subcritical Flow
K Sum by GR= 0
Std Step Tol= 0.01
Critical Tol= 0.01
Num of Std Step Trials= 20
Max Error Tol= 0.3
Flow Tol Ratio= 0.001
Split Flow NTrial= 30
Split Flow Tol= 0.02
Split Flow Ratio= 0.02
Log Output Level= 0
Friction Slope Method= 1
Unsteady Friction Slope Method= 2
Unsteady Bridges Friction Slope Method= 1
Parabolic Critical Depth
Global Vel Dist= 0 , 0 , 0
Global Log Level= 0
CheckData=True
Encroach Param=-1 ,0,0, 0
Mapping Interval=1HOUR
Computation Time Step Use Courant=        0
Computation Time Step Use Time Series=    0
Computation Time Step Count To Double=0
Computation Time Step Max Doubling=0
Computation Time Step Max Halving=0
Computation Time Step Residence Courant=0
Run HTab= 0
Run UNet= 0
Run Sediment= 0
Run PostProcess= 0
Run WQNet= 0
Run RASMapper=-1
UNET Theta= 0
UNET Theta Warmup= 0
UNET ZTol= 0
UNET ZSATol= 0
UNET MxIter= 0
UNET Max Iter WO Improvement= 0
UNET MaxInSteps= 0
UNET DtIC= 0
UNET DtMin= 0
UNET MaxCRTS= 0
UNET WFStab= 0
UNET SFStab= 0
UNET WFX= 1
UNET SFX= 1
UNET Gravity=32.17405
UNET 1D Methodology=Finite Difference
UNET DSS MLevel= 1
UNET Pardiso=0
UNET DZMax Abort= 0
UNET Use Existing IB Tables= 0
UNET Froude Reduction=False
UNET Froude Limit= 0
UNET Froude Power= 0
UNET D1 Cores= 0
UNET WindReference=Eulerian
UNET WindDragFormulation=Hsu (1988)
UNET D2 Coriolis=0
UNET D2 Cores= 0
UNET D2 Theta= 1
UNET D2 Theta Warmup= 1
UNET D2 Z Tol= 0.01
UNET D2 Volume Tol= 0.01
UNET D2 Max Iterations= 20
UNET D2 Equation= 0
UNET D2 RampUpFraction=0.1
UNET D2 TimeSlices= 1
UNET D2 Turbulence Formulation=Non-Conservative (original)
UNET D2 Eddy Viscosity=0.3
UNET D2 Transverse Eddy Viscosity=0.1
UNET D2 Smagorinsky Mixing=0
UNET D2 BCVolumeCheck=0
UNET D2 Cores=0
UNET D2 SolverType=PARDISO (Direct)
UNET D2 Minimum Iterations= 3
UNET D2 Maximum Iterations= 30
UNET D2 Restart Number= 10
UNET D2 Relaxation Coeff=1.3
UNET D2 SOR Precondition Iterations= 10
UNET D2 ILUT Maximum Fill= 8
UNET D2 ILUT Tolerance=1E-08
UNET D2 Convergence Tolerance=0.00001
UNET D1D2 MaxIter= 0
UNET D1D2 ZTol=0.01
UNET D1D2 QTol=0.1
UNET D1D2 MinQTol=1
Write IC File= 0
Write IC File at Fixed DateTime=0
Write IC File at Sim End=0
Echo Input=False
Echo Parameters=False
Echo Output=False
Write Detailed= 0
HDF Write Warmup=0
HDF Write Time Slices=0
HDF Flush=0
HDF Compression= 1
HDF Chunk Size= 1
HDF Spatial Parts= 1
HDF Use Max Rows=0
HDF Fixed Rows= 1
Calibration Method= 0
Calibration Iterations= 20
Calibration Max Change=0.05
Calibration Tolerance=0.2
Calibration Maximum=1.5
Calibration Minimum=0.5
Calibration Optimization Method= 1
WQ AD Non Conservative
WQ ULTIMATE=-1
WQ Max Comp Step=1HOUR
WQ Output Interval=15MIN
WQ Output Selected Increments= 0
WQ Create Restart=0
WQ Fixed Restart=0
WQ System Summary=0
WQ Write To DSS=0
Sorting and Armoring Iterations= 10
XS Update Threshold= 0.02
Bed Roughness Predictor= 0
Hydraulics Update Threshold= 0.02
Energy Slope Method= 1
Volume Change Method= 1
Sediment Retention Method= 0
Sediment TS Multiplier= 1
Warm Up Method= 0
XS Weighting Method= 0
Number of US Weighted Cross Sections= 1
Number of DS Weighted Cross Sections= 1
Upstream XS Weight=0
Main XS Weight=1
Downstream XS Weight=0
Number of DS XS's Weighted with US Boundary= 1
Upstream Boundary Weight= 1
Weight of XSs Associated with US Boundary= 0
Number of US XS's Weighted with DS Boundary= 1
Downstream Boundary Weight= 0.5
Weight of XSs Associated with DS Boundary= 0.5
Percentile Method= 0
Sediment Output Level= 3
Mass or Volume Output= 0
Output Increment Type= 1
Profile and TS Output Increment= 1
Transport Output Increment 1
XS Output Flag= 0
XS Output Increment= 10
Read HDF5 Sediment Hotstart= 0
Sediment Hotstart Type= 0
Write Gradation File= 0
Read Gradation Hotstart= 0
Write HDF5 File= 1
Write Binary Output= 1
Write DSS Sediment File= 0
DSS Sediment Output Type= 1
SV Curve= 0
Specific Gage Flag= 0
Subcell Erosion Methods= 0
Subcell Deposition Methods= 0
Advection Scheme= 1
Matrix Solver= 0
Implicit Weighting Factor= 1
Maximum Outer Loop Convergence Iterations= 5
Convergence Maximum Absolute= 0.001
Convergence RMSE= 0.0001
Grain Fractions Max Abs Error= 0.001
Max Subgrid Regions= 1
Max Subgrid Length Scale= 3.402823E+38
Initial Layer Thickness= 3.402823E+38
Min Layer Thickness= 3.402823E+38
Max Layer Thickness= 3.402823E+38
Number of Layers= 5

--- SLABCPFKT1.f01 (steady flow) ---

Flow Title=Flows
Program Version=6.31
Number of Profiles= 1
Profile Names=01pct
River Rch & RM=SLABCPFKT1,Main,1430
     149
Boundary for River Rch & Prof#=SLABCPFKT1,Main            , 1
Up Type= 0
Dn Type= 3
Dn Slope=0.00251
DSS Import GetInterval= 0
DSS Import GetPeak= 0
DSS Import FillOption= 0

--- SLABCPFKT1.g01 (geometry) ---

Geom Title=Geometry
Program Version=6.31

River Reach=SLABCPFKT1      ,Main
Reach XY= 30
2163597.96188617690143.4910312032163597.78157143690111.745454545
2163578.93162643690094.6742779542163559.90136669690087.641355876
2163525.56415889690093.0194727592163518.53123681690083.504342889
2163530.94227577690049.1671350962163496.19136668690030.550576653
2163504.46539266690003.2462909382163493.70915889689983.802329898
2163501.98318486689928.780057169 2163492.0543537 689883.27291431
2163453.53401299689802.5602987012163432.48136668  689789.7764208
2163428.75805499689745.0966805392163413.45110694689728.962329889
2163387.38792512689646.6357714442163356.15344156689608.655844156
2163334.22824675689544.189922078 2163330.7108472689504.322524686
2163314.99019785 689470.812719492163286.37057959689446.852587229
2163282.72956039689414.8178155852163233.07013663689301.963575495
2163221.90020156689243.8799131562163193.11201526  689210.2448484
2163151.71719704689123.6344877042163170.29298733688985.944392817
2163192.06584222688946.917636648     2163219.235      688924.308

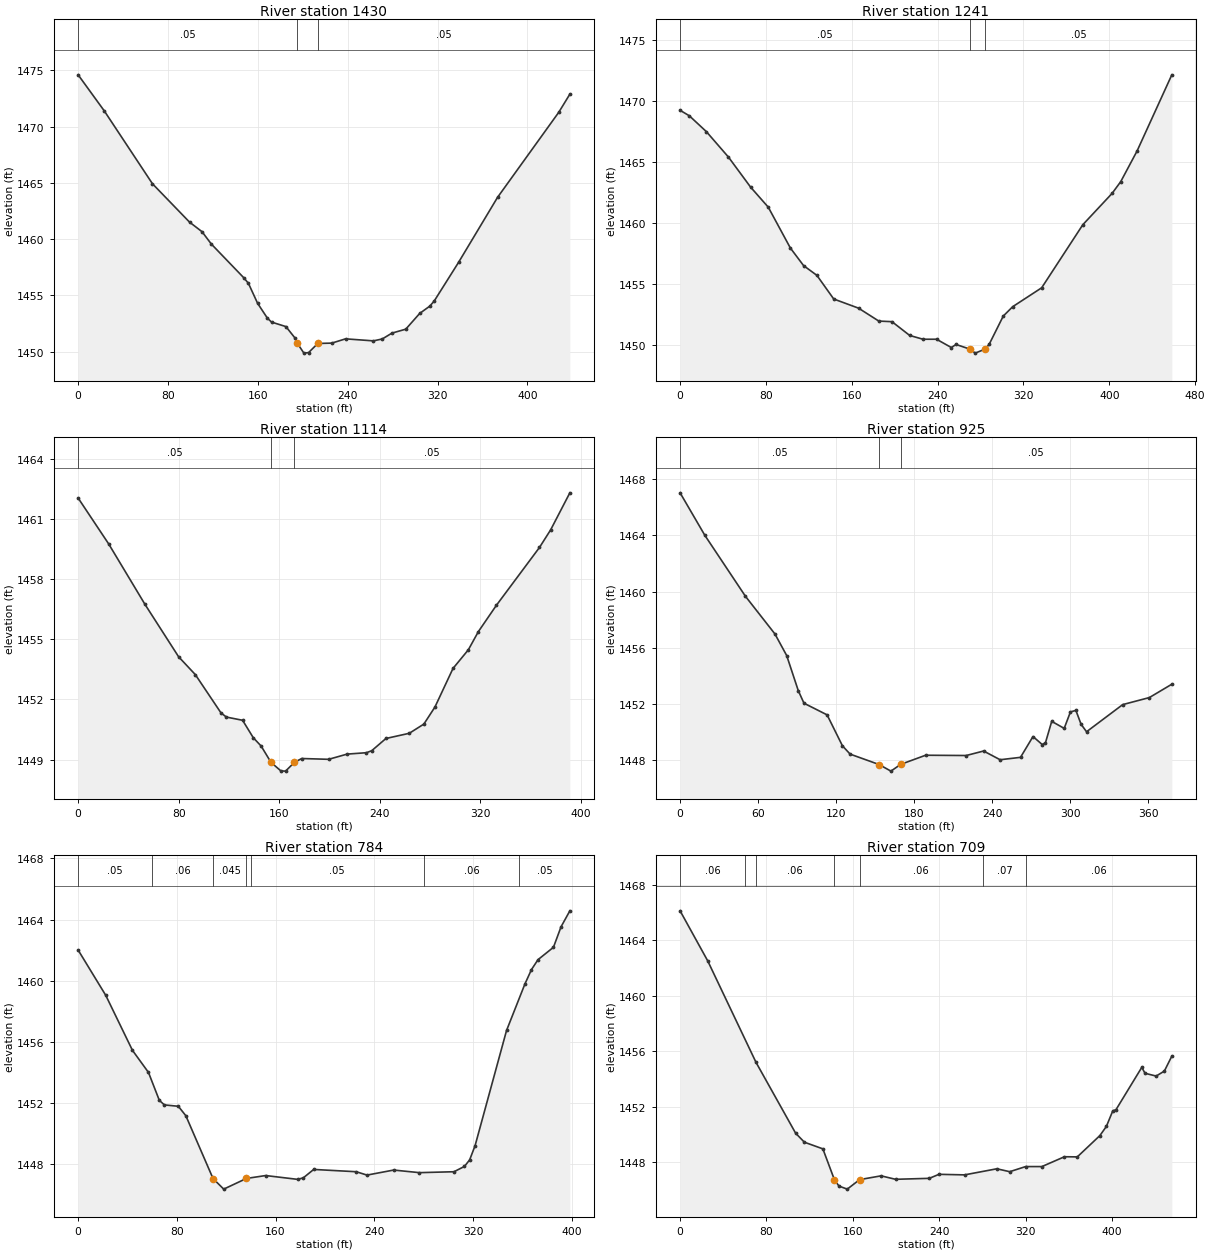
Type RM Length L Ch R = 1 ,1430    ,189.3,189.3,189.3
XS GIS Cut Line= 3
2163799.24727778690076.0389695972163501.92426686690150.116625038
2163380.74691185690201.009082476
#Sta/Elev= 30
       0 1474.61    23.3  1471.4    66.2 1464.92    99.2 1461.51   110.3 1460.66
   118.6 1459.56   147.4 1456.57   151.6 1456.07   159.8 1454.29   168.5 1452.97
   172.2 1452.62     185 1452.22   192.8 1451.24  195.27 1450.72     201 1449.86
   205.2 1449.91   213.4 1450.72   225.8 1450.75   238.1 1451.13   262.9 1450.95
   270.8 1451.12   279.4 1451.64   291.7 1451.99   304.1 1453.39   313.1 1454.04
     317 1454.49   338.7 1457.93   373.4 1463.71     428 1471.29   437.8 1472.89
#Mann= 3 ,-1,0
       0     .05       0  195.27    .045       0   213.4     .05       0
Bank Sta=195.27,213.4
XS Rating Curve= 0 ,0
Exp/Cntr=0.3,0.1

Type RM Length L Ch R = 1 ,1241    ,126.1,127,124.5
XS GIS Cut Line= 4
2163759.96689051 690062.702941732163540.13731207690008.500080487
2163462.68421683690044.1817897022163346.48750255690133.567894344
#Sta/Elev= 30
       0 1469.26     8.6 1468.81    24.5 1467.51    45.1 1465.42    65.7 1462.96
    82.2 1461.31   102.8 1457.96   115.1 1456.52   127.5 1455.72   143.2 1453.78
   166.3 1453.03   185.2 1451.97   197.5 1451.92     214 1450.79   226.4 1450.48
     239 1450.48   252.8  1449.8   257.2 1450.05   270.4 1449.66   275.1 1449.34
   284.2 1449.67     288 1450.05   301.2 1452.38     310 1453.15     337  1454.7
   375.4 1459.88   402.6 1462.44   410.7 1463.41   425.9 1465.92   458.3 1472.17
#Mann= 3 ,-1,0
       0     .05       0   270.4    .045       0   284.2     .05       0
Bank Sta=270.4,284.2
XS Rating Curve= 0 ,0
Exp/Cntr=0.3,0.1

Type RM Length L Ch R = 1 ,1114    ,188.2,188.5,184.1
XS GIS Cut Line= 4
2163639.35576423 689830.485320882163566.04767891689883.201247398
2163400.48672219 689946.625096492163330.47338229690048.762204118
#Sta/Elev= 30
       0 1462.06    24.3 1459.77    53.2 1456.75      80 1454.13    93.3 1453.24
   113.7 1451.33     118 1451.12   130.9 1450.96   139.4 1450.09   145.7 1449.67
   153.5 1448.86   161.4 1448.43   165.1 1448.42   172.2 1448.86     178 1449.05
   199.4 1449.01   214.1 1449.27   229.5 1449.34   233.7 1449.44     245 1450.05
   263.6 1450.31   275.2 1450.77     284 1451.62   298.4 1453.55   310.6 1454.48
   318.6 1455.39   332.9  1456.7   367.2 1459.59   376.1 1460.47   391.4 1462.32
#Mann= 3 ,-1,0
       0     .05       0   153.5    .045       0   172.2     .05       0
Bank Sta=153.5,172.2
XS Rating Curve= 0 ,0
Exp/Cntr(USF)=0,0
Exp/Cntr=0.3,0.1

Type RM Length L Ch R = 1 ,925     ,140.4,141.1,141.6
XS GIS Cut Line= 5
2163554.89872849689655.3945292162163505.43353239689707.218061819
2163357.74456527689779.7031024152163321.88654186689833.739682388
2163311.30355908689910.304776393
#Sta/Elev= 30
       0 1467.02    19.1 1463.99    50.3 1459.66      73 1456.98      82 1455.45
    90.9 1452.96    95.3 1452.06   113.1 1451.23   124.9 1449.03   130.8 1448.44
  153.08  1447.7   162.2 1447.23   169.7 1447.71   188.9 1448.36   220.1 1448.34
   233.5 1448.66   246.2 1448.04   261.9 1448.21   271.5 1449.69   278.6 1449.12
   281.1 1449.25   285.9 1450.77   295.5 1450.27   300.3 1451.44   304.5 1451.55
   308.5 1450.56   312.7 1450.03   340.5 1451.96     361 1452.46   378.3 1453.41
#Mann= 3 ,-1,0
       0     .05       0  153.08    .045       0   169.7     .05       0
Bank Sta=153.08,169.7
XS Rating Curve= 0 ,0
Exp/Cntr=0.3,0.1

Type RM Length L Ch R = 1 ,784     ,76.1,74.9,71.6
XS GIS Cut Line= 3
  2163476.932767689576.1076590562163201.28068781689688.488240679
2163124.40335755689753.789800208
#Sta/Elev= 30
       0    1462    22.4 1459.03      44 1455.43      57 1453.98    65.8 1452.15
    69.9 1451.85    81.2 1451.76    87.3 1451.14  109.35 1447.02     118 1446.33
   136.4 1447.03     152 1447.22   177.9 1446.97   182.5 1447.07   190.9 1447.62
   225.4 1447.47   234.1 1447.25   255.7 1447.58   276.6 1447.41   304.6 1447.47
   313.1 1447.82   317.3 1448.25   321.7 1449.18   347.2 1456.73   362.1 1459.78
   367.4 1460.72   372.7 1461.37   385.2 1462.18   391.4 1463.53   398.5 1464.57
#Mann= 7 ,-1,0
       0     .05       0      60     .06       0  109.35    .045       0
   136.4     .06       0     140     .05       0     280     .06       0
  357.68     .05       0
Bank Sta=109.35,136.4
XS Rating Curve= 0 ,0
Exp/Cntr=0.3,0.1

Type RM Length L Ch R = 1 ,709     ,44.7,45.2,47.3
XS GIS Cut Line= 3
2163485.28690139689517.9538651272163367.04702763689540.168101801
2163067.21464604689689.474528306
#Sta/Elev= 30
       0 1466.14    25.6 1462.52    70.3 1455.19     107 1450.07   115.1 1449.42
   132.2 1448.94  142.851446.717   147.1 1446.25   154.8 1446.03  166.231446.717
   186.1 1446.99   199.5 1446.74   230.8 1446.81   239.7  1447.1   263.4 1447.06
   293.3  1447.5   305.2 1447.29     320 1447.66     335 1447.66   355.9 1448.37
   367.8 1448.36   388.7  1449.9   394.7 1450.56   400.6 1451.68   403.6 1451.77
   427.5 1454.83   430.5  1454.4   440.8  1454.2   448.4 1454.56   455.3 1455.64
#Mann= 7 ,-1,0
       0     .06       0      60     .05       0      70     .06       0
  142.85    .045       0  166.23     .06       0  280.31     .07       0
  320.31     .06       0
Bank Sta=142.85,166.23
XS Rating Curve= 0 ,0
Exp/Cntr=0.3,0.1

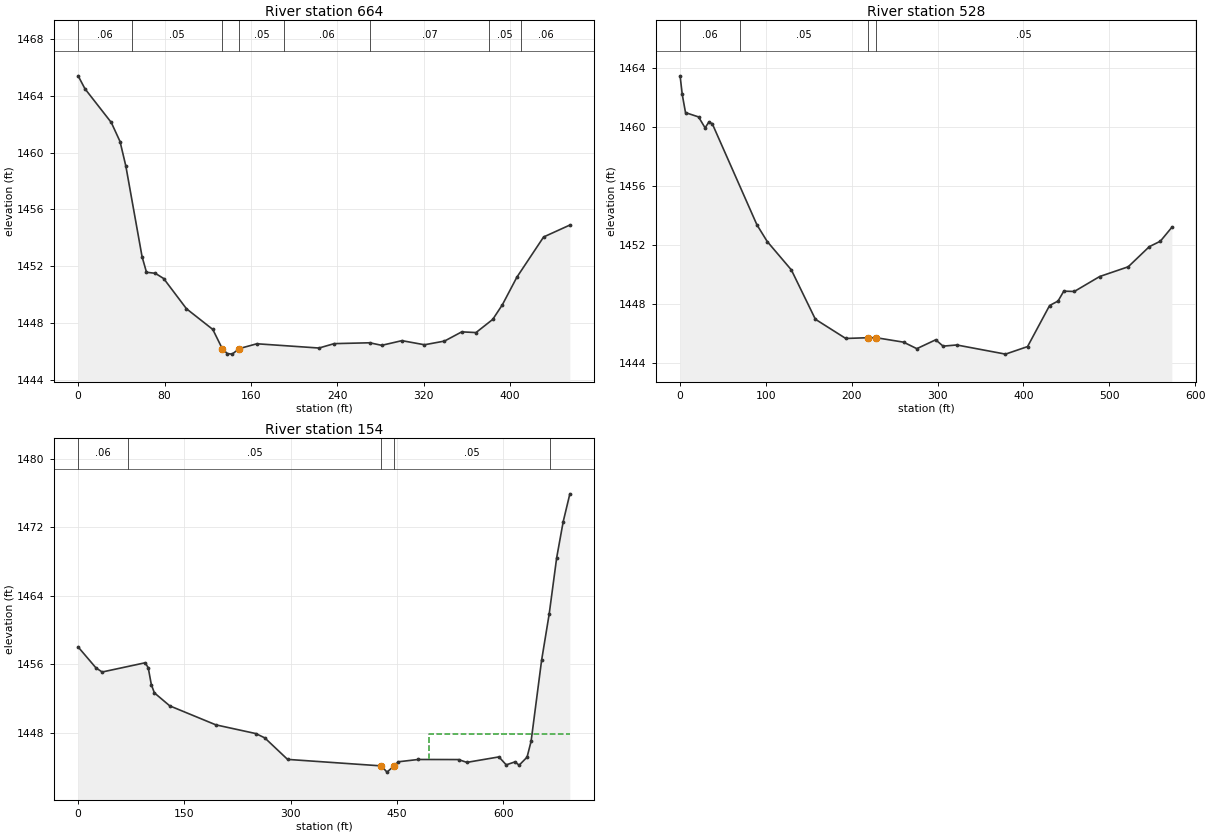
Type RM Length L Ch R = 1 ,664     ,133.7,136.5,135.3
XS GIS Cut Line= 3
2163470.35123307  689478.24200362163352.11135931689500.456240274
2163052.27897772 689649.76266678
#Sta/Elev= 30
       0 1465.41     6.3  1464.5    30.7 1462.12    38.8 1460.78    44.2 1459.04
    59.2 1452.66    63.3 1451.56    71.4 1451.49    79.2 1451.12   100.3 1448.99
   124.7 1447.53  133.421446.182   138.1 1445.83   142.6 1445.79  149.281446.182
   165.5 1446.52     223 1446.22   237.1 1446.53     270 1446.59   281.1 1446.41
   299.8 1446.74   320.7 1446.45   339.2 1446.71   355.2 1447.36   368.4 1447.31
   383.9 1448.24   392.8 1449.27   406.2 1451.21     431 1454.05   455.3 1454.89
#Mann= 8 ,-1,0
       0     .06       0      50     .05       0  133.42    .045       0
  149.28     .05       0  190.31     .06       0  270.31     .07       0
  380.31     .05       0  410.31     .06       0
Bank Sta=133.42,149.28
XS Rating Curve= 0 ,0
Exp/Cntr=0.3,0.1

Type RM Length L Ch R = 1 ,528     ,373.6,373.6,373.6
XS GIS Cut Line= 5
2163489.54800201689378.4958892832163329.20085697689369.378766649
2163251.80698407689407.4880273142163074.98196746689474.613731159
2163036.30340623689605.942919965
#Sta/Elev= 30
       0 1463.46     2.5  1462.2     6.3 1460.97    21.5 1460.68    29.1 1459.94
    33.4 1460.32    37.4 1460.23    89.5 1453.38   101.5 1452.25   129.6 1450.33
   157.6 1446.99     193 1445.69  218.65 1445.74   228.6 1445.74   260.3 1445.44
   275.8    1445   297.8  1445.6   306.4 1445.17   322.3 1445.25   379.1 1444.63
   404.8 1445.14   430.5 1447.92   440.3 1448.22     447 1448.89   459.3 1448.87
   488.8 1449.88   522.1 1450.54   546.6  1451.9   559.5 1452.27   572.9 1453.21
#Mann= 4 ,-1,0
       0     .06       0      70     .05       0  218.65    .045       0
   228.6     .05       0
Bank Sta=218.65,228.6
XS Rating Curve= 0 ,0
Exp/Cntr=0.3,0.1

Type RM Length L Ch R = 1 ,154     ,,,
XS GIS Cut Line= 4
2163579.41097878689171.7868105472163341.32936389689072.004717984
2163114.81122795689055.6310051132162958.22798843688917.913366009
#Sta/Elev= 30
       0 1458.02    25.2 1455.57    33.9 1455.09    94.6 1456.17    98.9 1455.59
   103.3 1453.61   107.6 1452.65   129.3 1451.13   194.3 1448.91   250.7 1447.89
   263.3 1447.39   295.5 1444.87   427.7 1444.11   435.8 1443.38   445.5 1444.09
   451.8 1444.59   479.9 1444.86   536.7 1444.85   548.4 1444.52   593.7 1445.16
     604 1444.23   616.4 1444.58   622.2 1444.19   633.4 1445.13   639.1 1446.99
   653.9 1456.45   664.6 1461.86   675.2 1468.46   684.4 1472.68   693.8 1475.93
#Mann= 5 ,-1,0
       0     .06       0      70     .05       0   427.7    .045       0
   445.5     .05       0  665.26      .1       0
#XS Ineff= 2 , 0
                          495.41         1447.81
Permanent Ineff=
       F       F
Bank Sta=427.7,445.5
XS Rating Curve= 0 ,0
Exp/Cntr=0.3,0.1
LCMann Table=0

Chan Stop Cuts=-1
Use User Specified Reach Order=0
Composite Channel Slope=5